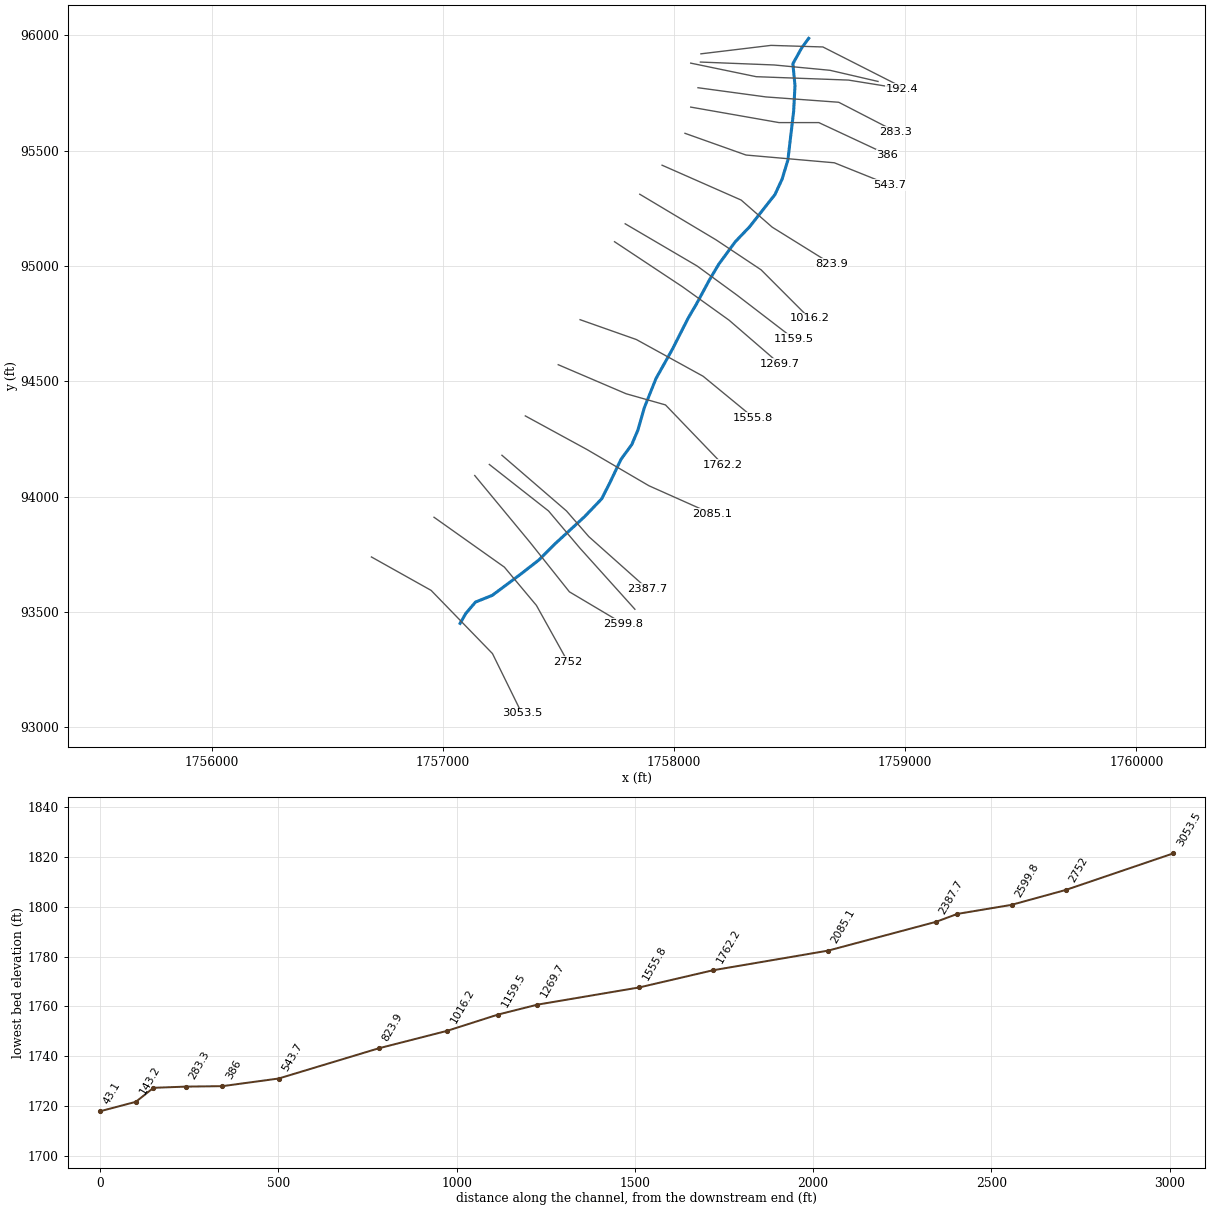
--- Big Branch A Trib 1.prj (project) ---

Proj Title=Big Branch A Trib 1
Current Plan=p01
Default Exp/Contr=0,0
English Units
Geom File=g01
Flow File=f01
Plan File=p01
BEGIN DESCRIPTION:
END DESCRIPTION:
DSS Export Rating Curves= 0
DSS Export Rating Curve Sorted= 0
DSS Export Volume Flow Curves= 0
DXF OffsetX= 0
DXF OffsetY= 0
DXF ScaleX= 0
DXF ScaleY= 0

--- Big Branch A Trib 1.p01 (plan) ---

Plan Title=Floodplain
Program Version=4.00
Geom File=g01
Flow File=f01
K Sum by GR=0
Std Step Tol=0.01
Critical Tol=0.01
Num of Std Step Trials=20
Max Error Tol=0.3
Flow Tol Ratio=0.001
Split Flow NTrial=30
Split Flow Tol=0.02
Split Flow Ratio=0.02
Log Output Level=0
Friction Slope Method=1
Unsteady Friction Slope Method=2
Unsteady Bridges Friction Slope Method=1
Global Log Level=0
CheckData=False
Run HTab=0
Run UNet=0
Run PostProcess=0
UNET Theta=0
UNET Theta Warmup=0
UNET ZTol=0
UNET ZSATol=0
UNET MxIter=0
UNET MaxInSteps=0
UNET DtIC=0
UNET DtMin=0
UNET MaxCRTS=0
UNET WFStab=0
UNET SFStab=0
UNET WFX=0
UNET SFX=0
UNET DSS MLevel=0
UNET DZMax Abort=0
UNET Convert EG Bridges=0
UNET Use Existing IB Tables=0
UNET Froude Limit=0
UNET Froude Power=0
Write IC File=0
Echo Input=False
Echo Output=False
Write Detailed=0

--- Big Branch A Trib 1.f01 (steady flow) ---

Flow Title=NFF Regression Equation
Program Version=4.00
Number of Profiles=1
Profile Names=P100yr
River Rch & RM=Big Branch A ...,Main      ,3053.5
644.3943
River Rch & RM=Big Branch A ...,Main      ,2387.7
658.2125
River Rch & RM=Big Branch A ...,Main      ,2085.1
761.6624
River Rch & RM=Big Branch A ...,Main      ,283.3
812.2623
Boundary for River Rch & Prof#=Big Branch A ...,Main      ,1
Up Type=0
Dn Type=3
Dn Slope=0.050706

--- Big Branch A Trib 1.g01 (geometry) ---

Geom Title=USGS 10m DEM
Program Version=4.00

River Reach=Big Branch A ...,Main
Reach XY= 30
     1757074.248       93450.953     1757099.172       93494.313
     1757140.855       93543.498     1757213.382       93572.676
     1757338.429       93666.044     1757415.124       93726.067
     1757486.818        93797.76     1757613.532       93914.471
     1757686.893       93991.166     1757722.739       94062.026
     1757770.257       94162.064     1757816.941       94226.254
     1757842.784        94287.11     1757871.962       94387.982
     1757921.635       94512.307     1757991.879       94638.054
     1758060.688          94774.     1758095.379       94833.148
     1758152.901       94939.855     1758193.582       95008.468
     1758264.358       95105.099     1758326.299       95169.941
      1758436.34       95309.994     1758467.185       95376.685
     1758492.194       95459.216     1758517.204       95670.962
     1758523.039       95782.671     1758513.869       95876.873
     1758552.217       95946.065     1758582.408       95987.192

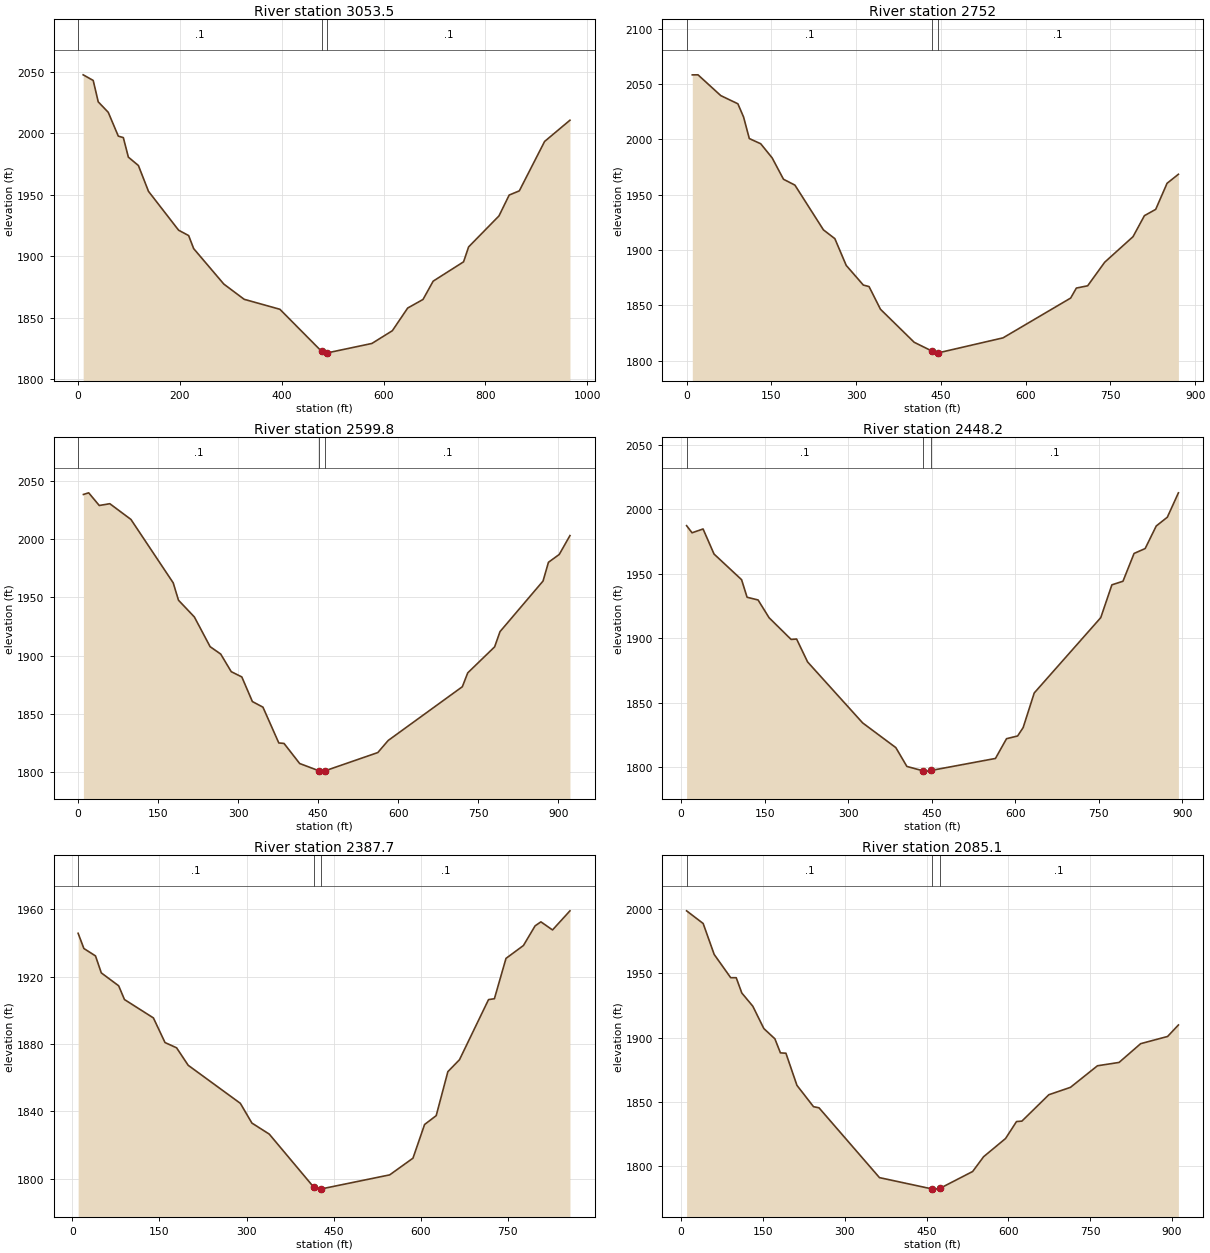
Type RM Length L Ch R = 1 ,3053.5  ,303,301.5,300
XS GIS Cut Line= 4
     1756690.722       93739.058     1756948.911       93594.221
     1757214.372       93320.218     1757341.442        93061.05
#Sta/Elev= 30
     9.9 2047.64    29.6 2043.08    39.5 2025.67    59.2 2017.13    78.9 1997.81
    88.8 1996.57    98.7 1980.69   118.4 1973.89   138.2 1952.91   197.4 1921.28
   217.1 1916.92     227  1906.3   286.2 1877.47   326.2 1865.08   396.4 1856.96
   478.4 1822.71   486.8 1821.31   488.4 1821.41   577.1 1829.17   617.3 1839.54
   647.4 1857.97   677.5 1864.95   697.5 1879.86   757.2 1895.56   767.1 1907.69
   826.8 1932.92   846.8 1949.87   866.7 1953.27   916.4 1993.46   966.2 2010.73
#Mann= 3 , 0 , 0
       0      .1       0   478.4    .045       0   488.4      .1       0
Bank Sta=478.4,488.4
XS Rating Curve= 0 ,0
Exp/Cntr=0.3,0.1

Type RM Length L Ch R = 1 ,2752    ,152.7,152.2,151.7
XS GIS Cut Line= 4
     1756961.505       93911.184     1757265.874       93694.977
     1757404.415       93529.149     1757540.856       93283.554
#Sta/Elev= 30
    10.1 2058.19    20.2 2058.24    60.5 2039.46    90.8 2032.05   100.9 2020.04
     111 2000.64   131.2 1995.92   151.4 1983.18   171.5 1963.84   191.7 1958.55
   242.2 1918.09   262.4 1910.15   282.5 1885.97   312.8 1868.19   322.9 1866.84
   343.1 1846.34   402.8 1816.47     435 1808.35   442.1 1806.67     445 1806.87
     560 1820.46   679.7 1856.45   689.8 1865.48   709.8 1867.54   739.9 1888.82
   790.1 1911.95   810.2 1930.92   830.2 1936.61   850.3 1960.18   870.4 1968.34
#Mann= 3 , 0 , 0
       0      .1       0     435    .045       0     445      .1       0
Bank Sta=435,445
XS Rating Curve= 0 ,0
Exp/Cntr=0.3,0.1

Type RM Length L Ch R = 1 ,2599.8  ,151,151.6,152.2
XS GIS Cut Line= 4
     1757137.658       94092.068     1757377.126       93802.031
     1757547.153       93587.923     1757781.125         93448.6
#Sta/Elev= 30
     9.9 2038.45    19.8 2039.87    39.6 2028.99    59.4 2030.52      99 2016.99
   178.2 1962.51   188.1 1947.59   217.8 1933.22   247.4 1907.65   267.2 1901.31
     287 1886.16   306.8 1881.64   326.6 1860.49   346.4 1855.66   376.1 1824.92
   385.9  1824.5   415.2 1807.25   452.2 1800.85   454.2  1800.7   462.2 1800.88
   561.6 1816.64   581.2 1827.06   720.1 1873.24   730.2 1885.14   780.6 1907.49
   790.7 1920.58   871.4  1964.1   881.5 1980.18   901.7  1986.9   921.8 2003.13
#Mann= 3 , 0 , 0
       0      .1       0   452.2    .045       0   462.2      .1       0
Bank Sta=452.2,462.2
XS Rating Curve= 0 ,0
Exp/Cntr=0.3,0.1

Type RM Length L Ch R = 1 ,2448.2  ,60.2,60.5,60.8
XS GIS Cut Line= 4
     1757200.802       94139.986     1757456.892       93938.473
     1757591.234       93778.941     1757830.531       93512.356
#Sta/Elev= 30
     9.9  1987.3    19.7 1981.77    39.5 1984.73    59.2  1965.3   108.6 1945.44
   118.5 1931.82   138.2 1929.72     158 1915.95   197.5 1899.14   207.4 1899.44
   227.1  1881.7   325.9 1834.46   385.5  1815.3   405.3 1800.73   435.1 1797.22
   444.8 1797.09  448.72 1797.61   564.3 1806.91   584.2 1822.23   604.1 1824.33
     614 1830.83   633.9 1857.66   753.3 1916.01   773.3 1941.44   793.2 1944.24
   813.1 1965.77     833 1969.55   852.9 1987.04   872.8 1993.84   892.7 2012.74
#Mann= 3 , 0 , 0
     9.9      .1       0   435.1    .045       0  448.72      .1       0
Bank Sta=435.1,448.72
XS Rating Curve= 0 ,0
Exp/Cntr=0.3,0.1

Type RM Length L Ch R = 1 ,2387.7  ,296,302.6,309.1
XS GIS Cut Line= 4
     1757255.379       94179.869     1757534.559       93938.473
     1757631.117        93827.22     1757885.108       93600.518
#Sta/Elev= 30
      10 1945.79    19.9 1936.76    39.9 1932.36    49.9 1922.28    79.8 1914.62
    89.8 1906.45   139.6 1895.55   159.6 1880.92   179.5  1877.8   199.5 1867.42
   289.3 1844.83   309.2 1833.11   339.1 1826.55  415.37 1795.17   418.2 1793.89
     428 1793.97   546.4 1802.35   586.5 1812.26   606.5 1832.26   626.5 1837.52
   646.6 1863.64   666.6 1870.73   716.6 1906.42   726.7 1906.94   746.7  1930.9
   776.7 1938.54   796.8 1950.22   806.8 1952.58   826.8 1947.78   856.8 1959.13
#Mann= 3 , 0 , 0
      10      .1       0  415.37    .045       0     428      .1       0
Bank Sta=415.37,428
XS Rating Curve= 0 ,0
Exp/Cntr=0.3,0.1

Type RM Length L Ch R = 1 ,2085.1  ,317.8,322.9,328
XS GIS Cut Line= 4
     1757356.404       94350.505     1757622.721       94205.058
     1757891.405       94047.625     1758162.439        93926.49
#Sta/Elev= 30
    10.1 1998.45    40.5  1988.6    60.7 1964.58      91 1946.52   101.1 1946.52
   111.3 1934.67   131.5 1924.39   151.7 1907.05     172 1899.06   182.1 1888.17
   192.2 1887.88   212.4 1862.94   242.8 1846.37   252.9 1845.48   363.7 1791.29
   460.7 1782.45   464.2 1782.36   474.2 1782.89   534.5 1796.05   554.6 1807.53
   594.8 1821.65   614.9 1834.82   624.8 1835.17   674.2 1855.66   713.8 1861.39
   763.3 1878.14   802.9 1880.73   842.5  1895.3   891.9  1900.9   911.7 1909.82
#Mann= 3 , 0 , 0
    10.1      .1       0   460.7    .045       0   474.2      .1       0
Bank Sta=460.7,474.2
XS Rating Curve= 0 ,0
Exp/Cntr=0.3,0.1

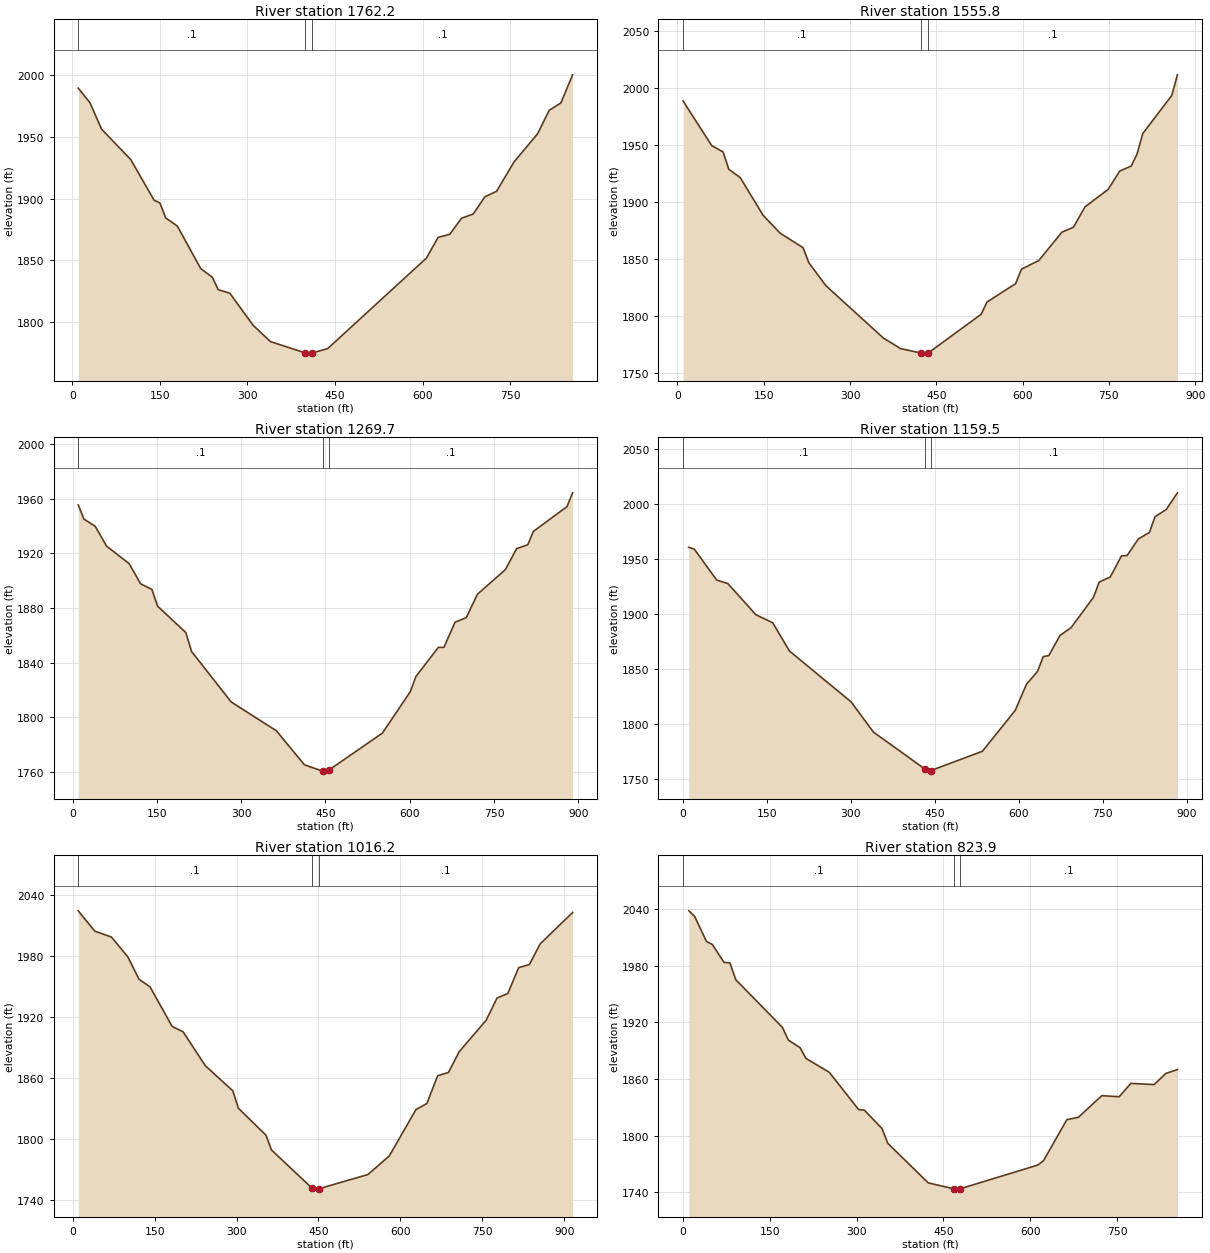
Type RM Length L Ch R = 1 ,1762.2  ,210.9,206.4,201.8
XS GIS Cut Line= 4
     1757498.874         94572.4     1757792.748       94446.454
     1757962.775       94398.175     1758212.567       94137.887
#Sta/Elev= 30
      10 1989.64      30 1977.89      50 1956.32    99.9  1931.7   139.9 1898.73
   149.9 1896.46   159.9 1884.22   179.8 1877.69   219.8 1843.17   239.8  1836.1
   249.8 1826.03   269.8 1823.13   309.7 1797.09   339.4 1783.88   398.3  1774.8
   408.1  1774.5   410.5 1774.56   437.6 1778.23   606.7 1851.67   626.7 1868.49
   646.8 1871.01   666.8 1883.99   686.9 1887.47   706.9 1901.43     727 1905.93
     757 1929.85   797.1  1952.5   817.1 1971.62   837.2 1977.67   857.2 2000.46
#Mann= 3 , 0 , 0
      10      .1       0   398.3    .045       0   410.5      .1       0
Bank Sta=398.3,410.5
XS Rating Curve= 0 ,0
Exp/Cntr=0.3,0.1

Type RM Length L Ch R = 1 ,1555.8  ,288.5,286.1,283.7
XS GIS Cut Line= 4
     1757593.334       94767.616     1757836.829       94681.553
     1758125.553       94522.418     1758342.711       94343.598
#Sta/Elev= 30
     9.9 1988.73    59.6 1949.67    79.5 1944.04    89.4 1928.85   109.3 1921.49
     149  1888.5   178.8 1872.74   218.5 1860.09   228.5 1846.91   258.3 1826.69
   358.2  1780.8   388.1 1771.62   423.4 1767.73   428.1 1767.64  436.34 1767.91
     528  1801.7     538 1812.37   587.9 1828.55     598 1841.27   628.1  1848.8
   668.3 1873.69   688.4    1878   708.5 1895.88   748.7 1911.17   768.8 1927.26
   788.9 1931.72   798.9 1942.07     809 1960.27   859.2 1993.47   869.2 2011.69
#Mann= 3 , 0 , 0
     9.9      .1       0   423.4    .045       0  436.34      .1       0
Bank Sta=423.4,436.34
XS Rating Curve= 0 ,0
Exp/Cntr=0.3,0.1

Type RM Length L Ch R = 1 ,1269.7  ,110.4,110.2,110.1
XS GIS Cut Line= 4
     1757742.369        95105.57     1758036.243       94910.354
     1758237.756       94765.517     1758456.062       94576.598
#Sta/Elev= 30
    10.1  1955.4    20.2 1945.05    40.3 1939.77    60.5 1925.27   100.8 1912.41
     121 1897.74   141.1 1893.61   151.2 1881.38   201.6 1862.03   211.7 1848.22
   282.2 1811.31   362.7 1790.22   412.4 1765.39  444.69 1760.74   452.2 1760.73
  455.61 1761.39   551.3 1788.55     601 1818.89   610.9 1829.91   650.7  1851.2
   660.7 1851.21   680.6 1869.66   700.5 1872.97   720.4 1890.09   770.2 1908.14
   790.1 1923.43     810 1926.29     820 1936.08   879.7 1954.15   889.7 1964.24
#Mann= 3 , 0 , 0
    10.1      .1       0  444.69    .045       0  455.61      .1       0
Bank Sta=444.69,455.61
XS Rating Curve= 0 ,0
Exp/Cntr=0.3,0.1

Type RM Length L Ch R = 1 ,1159.5  ,142.4,143.3,144.2
XS GIS Cut Line= 4
     1757788.549       95183.237     1758099.216       95000.616
     1758271.342        94874.67     1758516.936       94685.751
#Sta/Elev= 30
      10 1960.26      20  1958.6    60.1 1930.46    80.1 1927.21   130.1 1898.94
   160.2 1891.65   190.2 1865.92   300.3 1819.74   340.3 1792.21   432.9 1758.41
   437.9 1756.77   442.9  1757.3   534.9 1774.81   593.6 1811.98   613.6 1835.66
   633.6 1847.54   643.6 1860.84   653.6 1861.82   673.6 1880.09   693.6  1887.3
   733.6 1914.92   743.6 1928.62   763.6 1933.31   783.5 1952.48   793.5 1952.76
   813.5 1967.76   833.5 1973.84   843.5  1988.1   863.5 1994.62   883.5 2009.78
#Mann= 3 , 0 , 0
       0      .1       0   432.9    .045       0   442.9      .1       0
Bank Sta=432.9,442.9
XS Rating Curve= 0 ,0
Exp/Cntr=0.3,0.1

Type RM Length L Ch R = 1 ,1016.2  ,194.9,192.3,189.7
XS GIS Cut Line= 4
     1757851.511       95311.456     1758181.081       95113.967
     1758376.297       94983.823     1758585.653       94773.743
#Sta/Elev= 30
    10.1 2024.37    40.4 2004.36    70.8 1998.58   101.1 1978.85   121.3 1957.03
   141.6 1949.39     182 1910.54   202.2 1905.12   242.7 1871.88   293.2 1847.05
   303.3 1829.98   353.9 1803.34     364 1788.77  438.44 1751.09   442.9 1750.23
   451.7 1750.72   540.6 1764.61   579.7  1782.9   628.7 1828.68   648.5 1834.54
   668.3 1861.93     688 1865.11   707.8 1885.67   757.2 1916.67     777 1938.45
   796.8 1942.94   816.6 1968.36   836.3 1971.47   856.1 1991.86   915.4 2022.72
#Mann= 3 , 0 , 0
    10.1      .1       0  438.44    .045       0   451.7      .1       0
Bank Sta=438.44,451.7
XS Rating Curve= 0 ,0
Exp/Cntr=0.3,0.1

Type RM Length L Ch R = 1 ,823.9   ,267.6,280.2,292.9
XS GIS Cut Line= 4
     1757948.081       95437.228     1758290.234       95286.093
     1758424.576       95168.543     1758680.666       95009.012
#Sta/Elev= 30
    10.1 2038.42    20.2 2032.26    40.4 2005.92    50.5 2002.74    70.8 1983.72
    80.9 1983.28      91 1965.39   171.9 1914.59     182 1901.25   202.2 1893.28
   212.3  1881.9   252.7  1867.1   303.3 1827.63   313.4 1826.93   343.7  1807.5
   353.8 1791.82   423.6 1749.88   468.9 1743.41   473.2 1743.22   478.9 1743.62
   612.9 1768.72     623  1773.5   663.2 1816.87   683.3 1819.47   723.5 1842.35
   753.7 1841.24   773.8  1855.4     814  1854.1   834.2 1865.91   854.3    1870
#Mann= 3 , 0 , 0
       0      .1       0   468.9    .045       0   478.9      .1       0
Bank Sta=468.9,478.9
XS Rating Curve= 0 ,0
Exp/Cntr=0.3,0.1

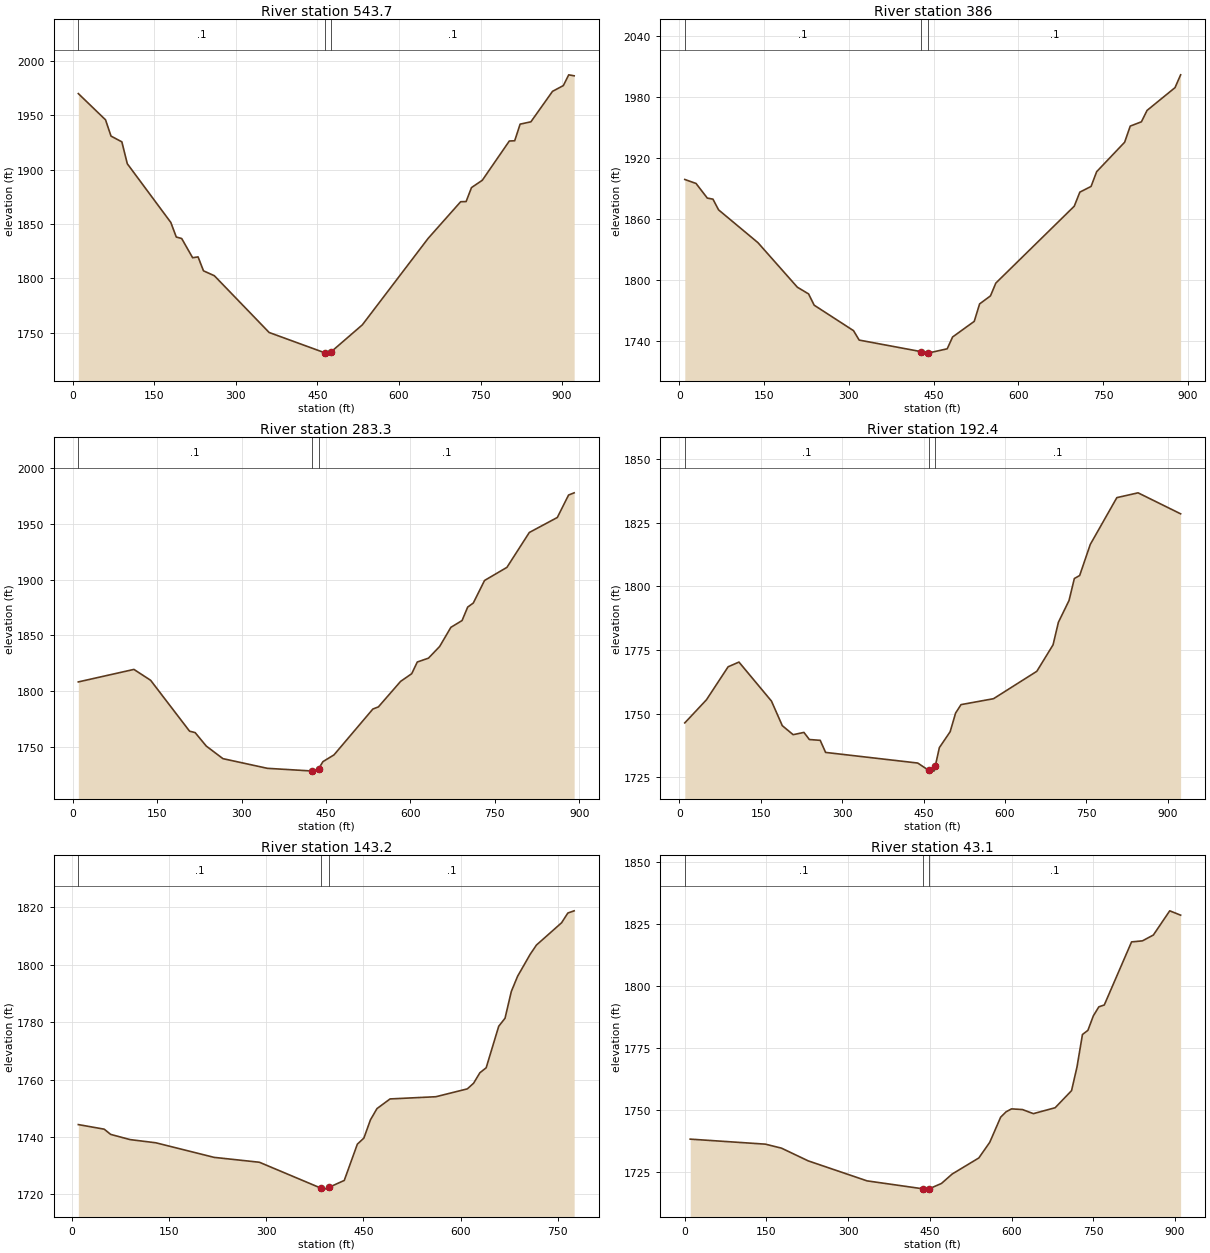
Type RM Length L Ch R = 1 ,543.7   ,156,157.7,159.5
XS GIS Cut Line= 4
     1758047.174       95575.437     1758311.225       95481.309
      1758693.26       95447.723     1758933.025       95351.332
#Sta/Elev= 30
      10 1969.85    60.1 1945.69    70.1 1930.79    90.1 1925.45   100.1 1905.33
   180.2 1851.32   190.2 1837.93   200.2 1836.55   220.3 1818.88   230.3 1819.66
   240.3 1806.83   260.3 1802.33   361.1 1750.12  464.31 1731.29   472.1 1731.14
   474.7 1732.15   532.6 1757.17   653.7 1836.72   713.5  1870.4   723.5 1870.53
   733.4 1883.39   753.3 1890.14     803 1926.23   812.9 1926.46   822.9 1941.76
   842.7 1943.89   882.5 1971.93   902.4 1977.21   912.3 1987.11   922.3 1986.21
#Mann= 3 , 0 , 0
      10      .1       0  464.31    .045       0   474.7      .1       0
Bank Sta=464.31,474.7
XS Rating Curve= 0 ,0
Exp/Cntr=0.3,0.1

Type RM Length L Ch R = 1 ,386     ,104.1,102.6,101.2
XS GIS Cut Line= 4
     1758071.928       95689.119     1758453.963       95621.948
     1758626.089       95621.948     1758922.062       95483.408
#Sta/Elev= 30
     9.9 1899.06    29.8 1895.14    49.7 1880.74    59.7 1879.69    69.6 1869.17
   139.2 1836.88   208.9 1793.03   228.8 1786.39   238.7  1775.3   308.3 1750.21
   318.3 1740.93  428.46 1729.49   435.7 1728.09   440.7  1728.2     474 1732.35
   483.5 1743.97   521.8 1759.37   531.3 1776.54   550.5 1784.46     560 1797.06
   698.7 1872.76   708.6 1886.61   728.4  1892.2   738.3 1906.72   787.8 1935.74
   797.7 1951.61   817.5 1955.85   827.4 1967.03   876.9 1989.48   886.8 2002.09
#Mann= 3 , 0 , 0
     9.9      .1       0  428.46    .045       0   440.7      .1       0
Bank Sta=428.46,440.7
XS Rating Curve= 0 ,0
Exp/Cntr=0.3,0.1

Type RM Length L Ch R = 1 ,283.3   ,90.2,90.9,91.6
XS GIS Cut Line= 4
     1758103.414       95773.083     1758397.288         95733.2
     1758712.152        95710.11     1758959.846       95582.065
#Sta/Elev= 30
     9.9 1808.07   108.7 1819.31   138.4 1809.53   207.6  1763.8   217.5 1762.51
   237.3 1750.41   266.9 1739.11   345.9 1730.42   424.6 1728.03   434.7  1727.9
   436.8  1729.9   444.6 1736.42   464.3 1742.51   533.4 1783.72   543.2 1785.62
   582.7 1808.57   602.4 1815.46   612.3 1825.95   632.2 1829.43   652.1 1839.95
     672 1857.11   691.9 1863.23   701.9 1875.33   711.9 1878.99   731.8 1899.22
   771.6 1911.01   811.4 1942.36   861.2 1955.85   881.2 1976.03   891.1    1978
#Mann= 3 , 0 , 0
     9.9      .1       0   424.6    .045       0   436.8      .1       0
Bank Sta=424.6,436.8
XS Rating Curve= 0 ,0
Exp/Cntr=0.3,0.1

Type RM Length L Ch R = 1 ,192.4   ,50.4,49.2,48
XS GIS Cut Line= 4
     1758071.928       95879.717     1758355.306       95820.942
     1758754.134       95806.248     1758986.082       95768.797
#Sta/Elev= 30
      10 1746.37    49.9 1755.45    89.8 1768.41   109.8 1770.27   169.7 1754.93
   189.6 1745.29   209.6 1741.74   229.5 1742.63   239.5 1739.84   259.5 1739.52
   269.4 1734.77   439.1  1730.6     459 1727.78     469 1727.42  471.67 1729.58
     479 1736.65   498.9 1742.91   508.9 1750.21   518.9 1753.55   578.8 1755.88
   658.6 1766.65   688.5 1777.05   698.3 1785.89   717.9 1794.45   727.7  1803.1
   737.5 1804.28     757 1816.47     806 1834.88   845.1 1836.77   923.5 1828.52
#Mann= 3 , 0 , 0
      10      .1       0     459    .045       0  471.67      .1       0
Bank Sta=459,471.67
XS Rating Curve= 0 ,0
Exp/Cntr=0.3,0.1

Type RM Length L Ch R = 1 ,143.2   ,97.8,100.1,102.8
XS GIS Cut Line= 4
     1758113.909       95884.335     1758432.972       95871.741
     1758674.368       95848.651     1758882.179       95800.371
#Sta/Elev= 30
      10 1744.32    49.9 1742.72    59.9  1740.9    89.8 1739.09   129.7 1737.97
   219.5 1732.89   289.4 1731.19  384.01  1722.2     390 1721.82   396.8 1722.44
   420.4 1724.85   440.6 1737.49   450.7 1739.62   460.8 1745.96   470.9 1749.89
   491.1 1753.26   561.8 1754.03   610.3 1756.76     620 1758.73   629.7 1762.38
   639.4 1764.11   658.8  1778.6   668.5 1781.38   678.2  1790.7   687.9 1796.02
   707.3 1803.67     717  1806.9   755.8 1814.67   765.5 1818.07   775.2 1818.83
#Mann= 3 , 0 , 0
      10      .1       0  384.01    .045       0   396.8      .1       0
Bank Sta=384.01,396.8
XS Rating Curve= 0 ,0
Exp/Cntr=0.3,0.1

Type RM Length L Ch R = 1 ,43.1    ,56.5,43.1,29.3
XS GIS Cut Line= 4
     1758116.009        95920.02     1758419.241       95956.648
     1758643.709       95949.812     1758982.936       95777.281
#Sta/Elev= 30
     9.9  1738.2   147.8 1736.18   177.4 1734.58   226.6 1729.44   334.7 1721.37
   438.2 1718.14   442.1 1718.04   448.2 1718.12   471.4 1720.33     491 1724.12
     540 1730.61   560.1 1736.94   580.1 1747.05   590.1 1749.23   600.1  1750.4
   620.1 1750.13   640.2 1748.48   680.2 1750.87   710.3 1757.76   720.3 1767.31
   730.3 1780.39   740.3 1782.07   750.3 1787.91   760.4 1791.55   770.4  1792.3
   820.5 1817.74   840.5 1818.16   860.5 1820.51   890.6 1830.27   910.6 1828.52
#Mann= 3 , 0 , 0
       0      .1       0   438.2    .045       0   448.2      .1       0
Bank Sta=438.2,448.2
XS Rating Curve= 0 ,0
Exp/Cntr=0.3,0.1

Chan Stop Cuts=-1
Use User Specified Reach Order=0